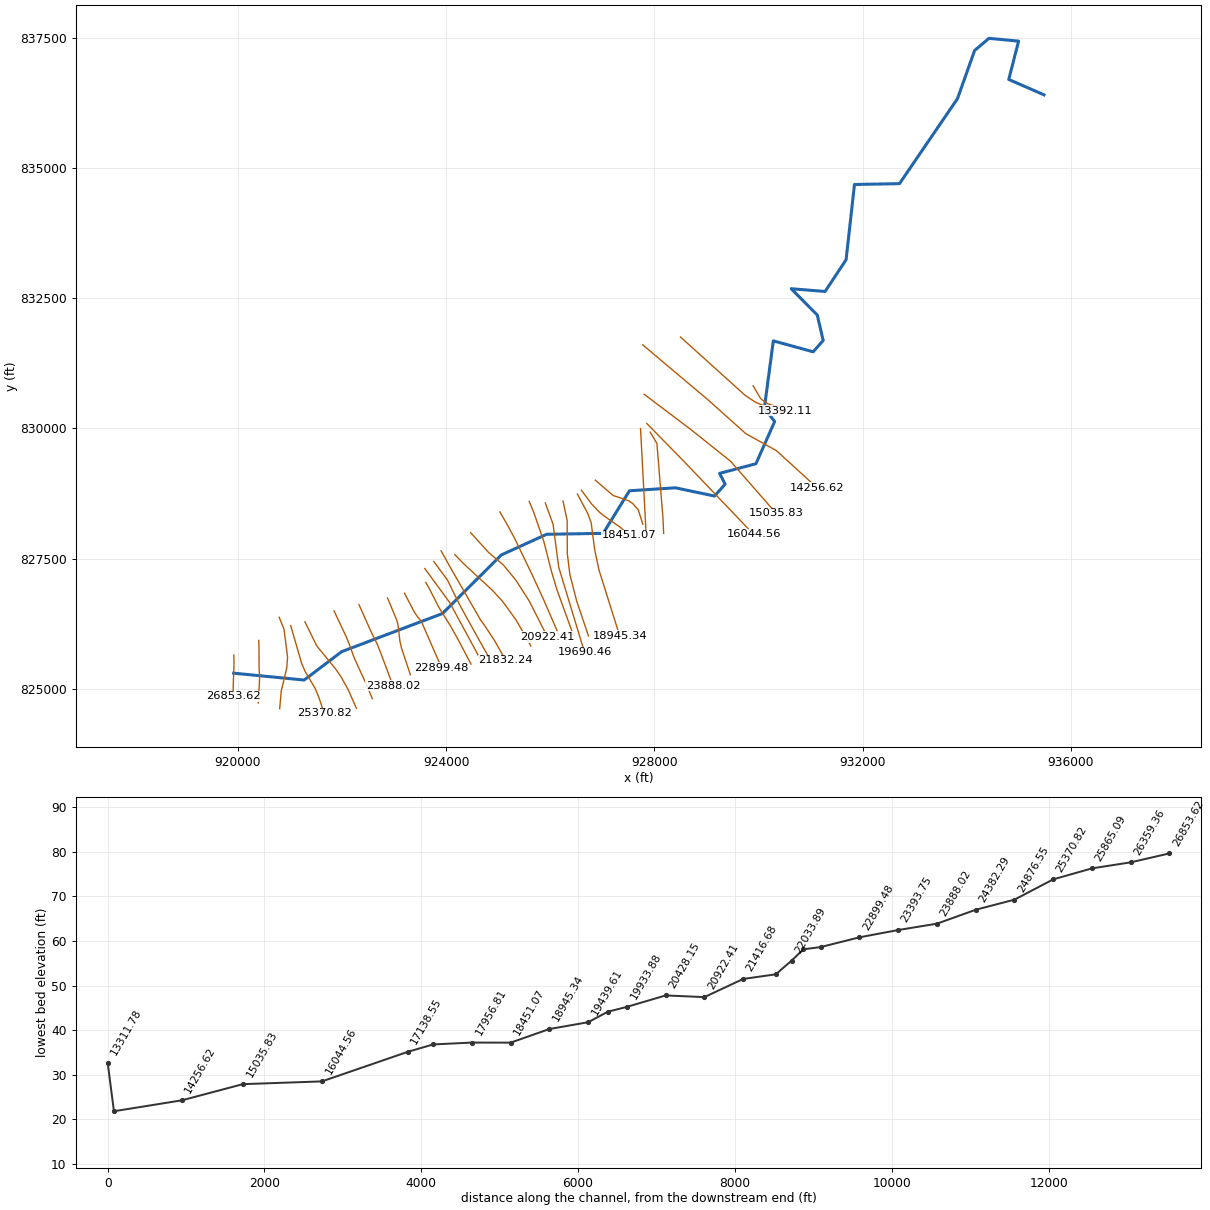
--- 16397_ras.prj (project) ---

Proj Title=16397
Current Plan=p01
Default Exp/Contr=0.3,0.1
English Units
Geom File=g01
Flow File=f01
Plan File=p01
Y Axis Title=Elevation
X Axis Title(PF)=Main Channel Distance
X Axis Title(XS)=Station
BEGIN DESCRIPTION:
RFD model 16397 exported to HEC-RAS
END DESCRIPTION:

--- 16397_ras.p01 (plan) ---

Plan Title=Plan 01
Program Version=4.10
Short Identifier=Plan 01
Geom File=g01
Flow File=f01
Subcritical Flow
Calc Critical at every XS
Secant Critical Depth

--- 16397_ras.f01 (steady flow) ---

Flow Title=Flow 01
Program Version=5.01
Number of Profiles= 6
Profile Names=10yr,25yr,50yr,100yr,100plus,500yr
River Rch & RM=16397,37,26853.62
  192.42  303.39   405.7  497.35  726.12 1220.47
River Rch & RM=16397,37,25370.82
  201.33  317.65  424.98  521.16   760.9 1271.46
River Rch & RM=16397,37,24876.55
  246.77  390.19  522.85  641.91  937.19 1524.12
River Rch & RM=16397,37,24382.29
  417.02  665.62  897.83 1108.05 1617.76 2462.84
River Rch & RM=16397,37,23888.02
  424.82  678.46  915.52 1130.27 1650.19 2507.02
River Rch & RM=16397,37,23393.75
  442.88  708.17  956.41 1181.57 1725.09 2608.38
River Rch & RM=16397,37,22899.48
  478.82   767.7 1038.71 1285.27 1876.49 2813.36
River Rch & RM=16397,37,22405.22
  488.89  784.53 1062.09 1314.85 1919.69 2872.03
River Rch & RM=16397,37,22185.45
  489.98  786.38 1064.69 1318.17 1924.53 2878.71
River Rch & RM=16397,37,21416.68
  782.96 1274.26 1741.78 2173.79 3173.74 4501.02
River Rch & RM=16397,37,20922.41
  804.01 1309.83 1791.59 2237.24 3266.37 4619.38
River Rch & RM=16397,37,20428.15
  811.96 1323.46 1810.87    2262 3302.53 4666.39
River Rch & RM=16397,37,19933.88
  817.37 1332.84 1824.22 2279.24 3327.69 4699.46
River Rch & RM=16397,37,19690.46
  821.44 1339.88 1834.23 2292.16 3346.56 4724.21
River Rch & RM=16397,37,19439.61
  823.24    1343 1838.67  2297.9 3354.93 4735.19
River Rch & RM=16397,37,18945.34
  827.28 1350.01 1848.64 2310.78 3373.73 4759.86
River Rch & RM=16397,37,18451.07
 1023.46 1688.15 2328.35 2928.67 4275.86 5914.94
River Rch & RM=16397,37,17956.81
 1031.27 1701.72  2347.7  2953.7  4312.4 5961.38
River Rch & RM=16397,37,17462.54
 1045.07 1725.74 2381.98  2998.1 4377.23 6043.88
River Rch & RM=16397,37,17138.55
 1056.15    1745 2409.47 3033.68 4429.18 6109.81
River Rch & RM=16397,37,16044.56
 1081.97    1790 2473.77 3117.03 4550.86 6264.22
River Rch & RM=16397,37,15035.83
  1140.5 1892.19 2619.98 3306.75 4827.85 6614.43
River Rch & RM=16397,37,14256.62
 1159.84 1925.97 2668.31 3369.46 4919.42 6729.55
River Rch & RM=16397,37,13392.11
 1272.63 2123.43 2951.36 3737.36 5456.55 7401.42
River Rch & RM=16397,37,13311.78
    1276 2129.29 2959.73 3748.22 5472.41 7420.99
River Rch & RM=16397,37,13266.25
 1276.79 2130.66  2961.7 3750.77 5476.13 7425.59
River Rch & RM=16397,37,12714.57
 1281.71 2139.25 2973.98 3766.71  5499.4 7454.31
River Rch & RM=16397,37,10798.83
 1316.71 2200.34 3061.42 3880.21 5665.11 7658.71
River Rch & RM=16397,37,9550.479
 1336.79 2235.47 3111.77 3945.64 5760.63 7776.49
River Rch & RM=16397,37,8372.829
 1370.33  2294.2 3195.98 4055.13 5920.49 7973.12
River Rch & RM=16397,37,7333.895
 1377.56 2306.87 3214.16 4078.78 5955.01 8015.56
River Rch & RM=16397,37,5926.177
  1441.7 2419.16 3375.21 4288.18 6260.75 8389.31
River Rch & RM=16397,37,       0
 1619.87 2731.77 3824.25 4872.85 7114.36 9422.53
Boundary for River Rch & Prof#=16397,37,1
Up Type= 0
Dn Type= 2
Boundary for River Rch & Prof#=16397,37,2
Up Type= 0
Dn Type= 2
Boundary for River Rch & Prof#=16397,37,2
Up Type= 0
Dn Type= 2
Boundary for River Rch & Prof#=16397,37,2
Up Type= 0
Dn Type= 2
Boundary for River Rch & Prof#=16397,37,2
Up Type= 0
Dn Type= 2
Boundary for River Rch & Prof#=16397,37,2
Up Type= 0
Dn Type= 2

--- 16397_ras.g01 (geometry) ---

Geom Title=16397
Program Version=4.10

River Reach=16397,37
Reach XY= 30
  919920.7747314825298.773883898921274.941398024825166.829439441
921995.872382406825712.465869176923931.484684995826444.359594497
925060.965703608827568.956175558925931.191398024 827966.09159223
927018.430981399827984.537772785 927521.90320358828801.595064457
 928404.06466195828859.103745003929158.187925818828700.683606093
929360.212236673828929.596244312929254.042958798829136.300555361
929951.781403364829321.056074003930311.616745295830131.890203325
 930113.04903695830385.796453331930285.936768414831681.514045892
931050.910726729831471.010573677931243.497928888831689.092570833
931129.469754547832178.692865349930629.469754549 832682.16508756
931280.511421205832630.081754218931683.289198965833239.456754211
   931844.583473834684.487502563932708.896837832834700.611268086
933823.117034617836333.562657068934151.242034614837257.173768168
934427.283701271837491.548768187934996.728145719 837437.72932374
934807.492034647836701.618212622 935484.57536796836406.479323745

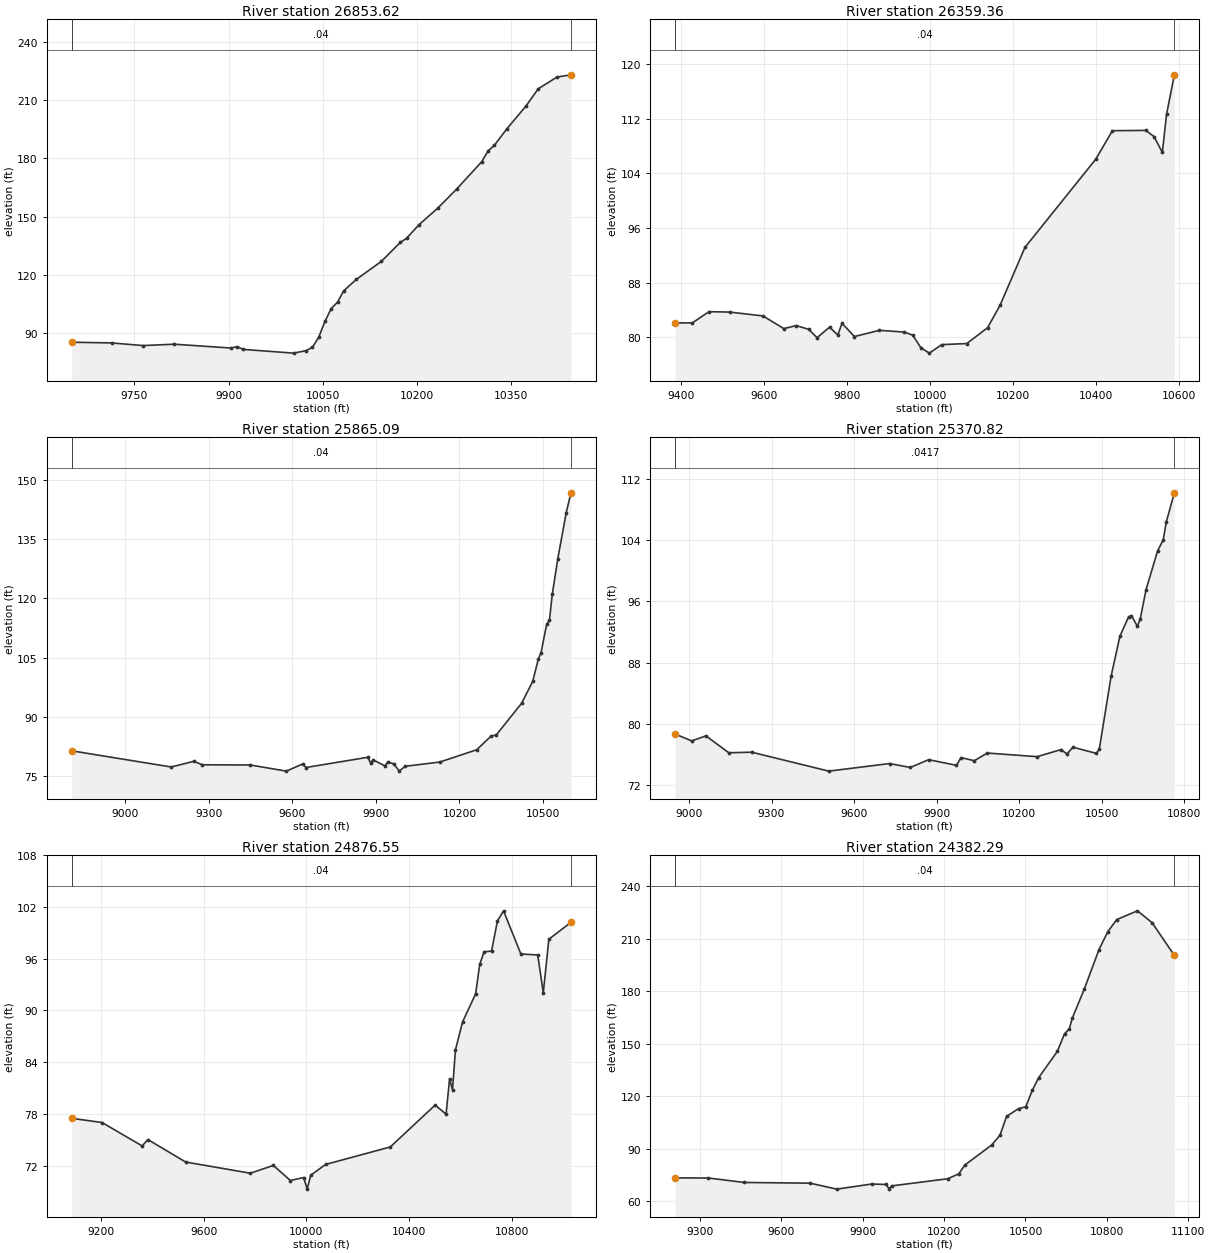
Type RM Length L Ch R = 1 ,26853.62,494.267600,494.267600,494.267600
XS GIS Cut Line= 6
919924.431937837825648.725131314919926.970909712825504.469581754
919924.895818734825371.446794467919914.367825067825111.654051733
919910.494568962824898.777210999919910.226193434824852.956054718
#Sta/Elev= 30
9649.88985.286099713.62484.925459763.63283.560389813.63984.26003 9903.6582.29272
9913.65182.972019923.65381.5791210003.7279.6641910023.7480.9342810033.7582.66878
10043.7587.7881710053.7695.9712310063.77102.638310073.78105.915810083.79111.8173
 10103.8117.654710143.83126.977810173.86136.706910183.86138.826610203.87145.9035
10233.87154.460710263.88164.271310303.89178.371710313.89183.924310323.89186.7668
10343.89 195.322 10373.9206.8515 10393.9 215.954 10423.9 221.96810445.95223.1053
#Mann= 3 , 0 , 0
9649.889    0.04       09649.889    0.04       010445.95    0.04       0
#XS Ineff= 2 , 0
       09769.405                       0
Bank Sta=9649.889,10445.95
Exp/Cntr=0.3,0.1

Type RM Length L Ch R = 1 ,26359.36,494.267500,494.267500,494.267500
XS GIS Cut Line= 6
920402.618143991 825926.65989887920407.506951215 825796.22219031
920409.140027721825429.618252766920418.458578213 825207.34586891
920415.296521541825107.678548484920392.657752767824726.199527363
#Sta/Elev= 30
9386.45182.088399428.16482.090739468.18483.730169518.20983.67042 9598.2183.10463
9648.21181.248099678.21181.694869708.21181.138719728.21279.920929758.21281.45507
9778.21280.324659788.21282.019079818.21280.092339878.21380.998239938.24480.74199
9958.26980.293659978.31278.430549998.35577.6589510028.4178.9076910088.4579.06076
10138.4781.3798110168.4884.6547110228.5493.1509710398.86106.065410438.93110.2366
10519.08110.284110539.11109.384410559.15107.050810569.16112.613510587.98118.4234
#Mann= 3 , 0 , 0
9386.451    0.04       09386.451    0.04       010587.98    0.04       0
#XS Ineff= 2 , 0
       0 9853.74                       0
Bank Sta=9386.451,10587.98
Exp/Cntr=0.3,0.1

Type RM Length L Ch R = 1 ,25865.09,494.267600,494.267600,494.267600
XS GIS Cut Line= 6
920794.480228531826372.617431065920888.938933679826139.684877995
920956.684694591825603.104812472920939.153476725825391.156904326
920834.390545495824955.267939488920804.823086591 824617.90510632
#Sta/Elev= 30
8806.857 81.44659164.72877.348429245.97378.794359276.30977.902869447.70477.86093
9577.95876.302869637.978 78.15369647.98177.21403  9870.179.802159880.39378.45463
9890.70479.117249931.94877.64054 9942.3378.570139963.124 78.19419983.91876.32224
 10004.777.5264510128.9778.5964810261.6381.7063310312.14 85.082210332.35 85.4798
10422.8593.44637   1046398.9994210483.04104.631610493.06106.3153 10513.1 113.497
10523.12114.431910533.14121.010610553.15 130.05110583.17141.661510600.27146.7377
#Mann= 3 , 0 , 0
8806.857    0.04       08806.857    0.04       010600.27    0.04       0
#XS Ineff= 2 , 0
       09891.624                       0
Bank Sta=8806.857,10600.27
Exp/Cntr=0.3,0.1

Type RM Length L Ch R = 1 ,25370.82,494.267500,494.267500,494.267500
XS GIS Cut Line= 6
921016.525988113826213.271945106921224.310793512825492.783115128
921292.375007781825334.218523117 921482.74984799825011.976580339
921551.177730843824850.575698704921661.715750075824526.672086705
#Sta/Elev= 30
8949.19178.680939009.67177.781779061.565 78.43829144.59676.230759227.62776.30739
 9508.0773.835699728.96674.825389804.41874.312119870.96275.329379972.08774.59263
9988.86975.5975410037.1275.1947410084.4476.1954810265.1575.7215510352.3376.64767
10373.9276.0700210395.5276.9593310481.1176.1456310491.7676.7787710534.3986.22389
10566.2591.4308610597.9193.9762710608.4794.1267910629.5892.7396410640.13 93.6567
10661.2497.4992310703.16102.5524 10724.1104.043410734.56106.291110764.21110.1496
#Mann= 3 , 0 , 0
8949.191  0.0417       08949.191  0.0417       010764.21  0.0417       0
#XS Ineff= 2 , 0
       09863.985                       0
Bank Sta=8949.191,10764.21
Exp/Cntr=0.3,0.1

Type RM Length L Ch R = 1 ,24876.55,494.267600,494.267600,494.267600
XS GIS Cut Line= 6
921289.147249673826286.226930594921516.073002608825824.483055363
921886.229617423825370.264033797921985.433398968825224.623526517
922115.833149102824990.116006215922278.488235523824625.260118373
#Sta/Elev= 30
9084.73677.492389203.253 77.00589359.72574.285729381.97975.027849529.40672.42138
9781.53971.12352 9871.2972.028869937.68670.278529989.394 70.624310003.07 69.2784
10016.9670.8960410075.1972.1422610327.2374.1711310502.0479.0264510544.7177.97202
10558.3982.1009610569.7180.7874410581.03 85.394810608.7288.6639910659.7391.92035
10675.9195.3518810693.0496.80842 10721.996.88544 10744.9100.386310768.67101.5574
10836.27 96.549410901.9596.4411110923.6692.0478810945.3598.2619311031.43100.2215
#Mann= 3 , 0 , 0
9084.736    0.04       09084.736    0.04       011031.43    0.04       0
#XS Ineff= 2 , 0
       09770.483                       0
Bank Sta=9084.736,11031.43
Exp/Cntr=0.3,0.1

Type RM Length L Ch R = 1 ,24382.29,494.267500,494.267500,494.267500
XS GIS Cut Line= 6
921848.521558234826495.374697534922080.424591451826002.971957683
922134.716950406825871.938432654922234.641713564825596.270207054
922445.819486724825136.259553673922584.949878564824809.137104198
#Sta/Elev= 30
9207.76273.412519330.00173.36945  9462.970.818329705.82770.40792 9803.9867.00885
9933.18569.929589986.02569.672359996.54767.2265410007.0868.8705710212.72 72.9253
10254.24 75.708410276.1280.7137810375.1392.1468910406.05 97.823710430.24108.5461
10474.33112.964410501.17114.028410524.96 123.35910548.74130.673210617.61145.6672
10643.86155.6382 10661.7158.554910672.72164.687610716.58181.081110771.14203.7895
10803.88214.063510836.62220.894310912.91225.881710966.93219.111611048.88200.4422
#Mann= 3 , 0 , 0
9207.762    0.04       09207.762    0.04       011048.88    0.04       0
#XS Ineff= 2 , 0
       0                               0
Bank Sta=9207.762,11048.88
Exp/Cntr=0.3,0.1

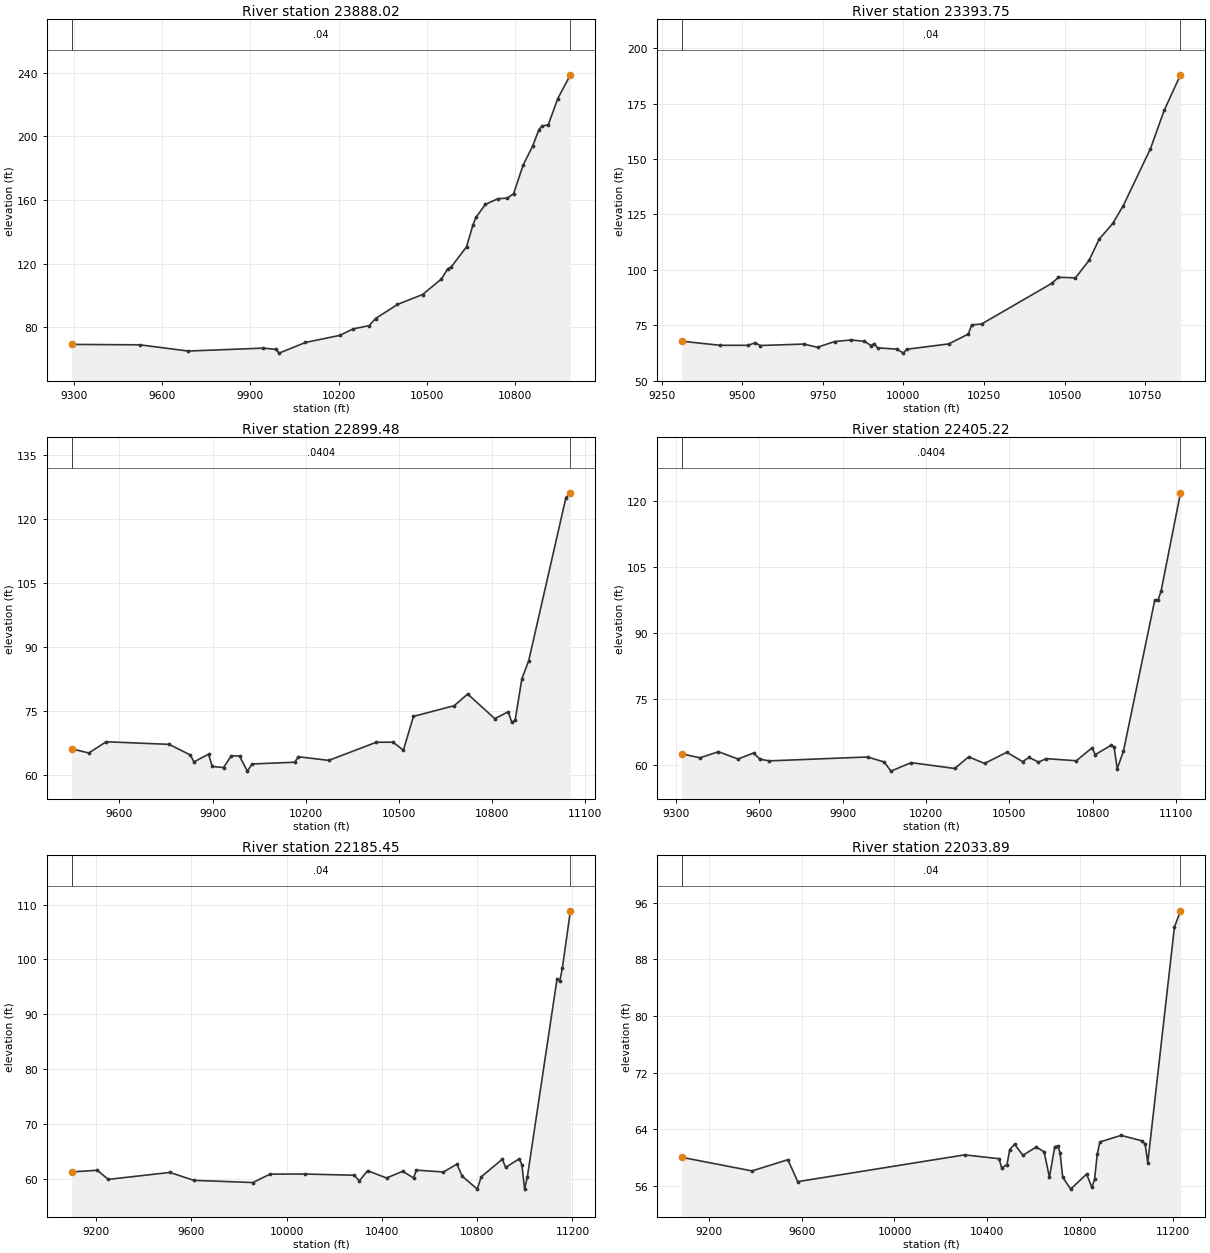
Type RM Length L Ch R = 1 ,23888.02,494.267600,494.267600,494.267600
XS GIS Cut Line= 6
922327.492164615826616.803865349922551.828958283826112.132847016
922650.515519596825914.353018938922687.046022359825833.609377575
922751.873751264825670.240860504922981.904995292825054.694022833
#Sta/Elev= 30
9292.91269.360739524.96869.092679688.98665.191689944.81567.03118 9986.8966.23304
9998.14863.8828710087.5170.5862710203.5674.9959110250.2279.1389410304.0181.13296
10325.5385.5820610400.2494.4413510485.58 100.68710549.58110.448610570.92116.8383
10581.58117.682710634.92130.669610656.25144.155810666.92149.108910698.92157.2815
 10741.8160.855510773.64  161.2110795.02164.079110827.09181.930510859.16193.7016
10880.54204.098210891.23206.490510912.61 207.21610944.69223.643510987.77238.6146
#Mann= 3 , 0 , 0
9292.912    0.04       09292.912    0.04       010987.77    0.04       0
#XS Ineff= 2 , 0
       09467.642                       0
Bank Sta=9292.912,10987.77
Exp/Cntr=0.3,0.1

Type RM Length L Ch R = 1 ,23393.75,494.267500,494.267500,494.267500
XS GIS Cut Line= 6
922876.296375578 826743.48204989923053.760994084826316.959998229
  923076.0832811826234.544453174923114.368470784825913.019083352
923144.476384049825781.112974786923315.316013511825267.387258593
#Sta/Elev= 30
9311.54967.837279430.66865.991159518.16265.992419539.82767.13106 9554.9265.88954
9690.87566.544329733.34965.107629786.13367.670849837.93568.404419878.94867.78283
9899.23165.887279909.37266.730829919.51364.834079979.808 64.27299999.878 62.4592
10009.9164.1981510140.72 66.621910201.5571.0757610211.76 75.2199 10242.475.57379
10460.2593.9175110481.34 96.674110534.0596.4168210576.23104.293310607.86113.9198
10650.04120.999310682.48129.016710766.88154.689910809.41171.962710860.03188.0113
#Mann= 3 , 0 , 0
9311.549    0.04       09311.549    0.04       010860.03    0.04       0
#XS Ineff= 2 , 0
       09834.294                       0
Bank Sta=9311.549,10860.03
Exp/Cntr=0.3,0.1

Type RM Length L Ch R = 1 ,22899.48,494.267600,494.267600,494.267600
XS GIS Cut Line= 6
 923202.00253007 826834.47003033923394.873505937826465.320936288
923456.893728288826376.050150361923501.211362773826327.113410756
923536.028266531826268.474909809923914.660740554825401.774169839
#Sta/Elev= 30
9446.36366.040069501.72765.078949557.68567.703929760.06267.095199828.61264.60256
9840.18562.983179887.16964.787789899.08361.918799935.47161.662089960.51964.43052
9986.87764.3412210012.1660.8201510027.6762.5019610164.84 62.905210175.8364.19161
10274.2763.3388510426.91  67.58410481.4267.6040310514.1365.7104910546.8473.64853
10677.6776.1499210721.29   78.8810808.5173.1175610851.9774.7319710863.0272.25335
10873.9372.7123510895.7382.4802510917.5486.6529711037.47124.910611051.89126.0314
#Mann= 3 , 0 , 0
9446.363  0.0404       09446.363  0.0404       011051.89  0.0404       0
#XS Ineff= 2 , 0
       0                10758.58       0
Bank Sta=9446.363,11051.89
Exp/Cntr=0.3,0.1

Type RM Length L Ch R = 1 ,22405.22,219.770200,219.770200,219.770200
XS GIS Cut Line= 6
 923610.54302226 827042.78959796923682.556636864826913.564373299
923866.306757063826555.013656209924085.158476173 826205.82626811
 924261.17697211825889.261401406924479.195281436825472.401958153
#Sta/Elev= 30
 9320.9662.560249387.11761.660519453.37363.045559523.623 61.38689579.96762.75111
9602.48161.361179635.98860.962029990.00261.8467310050.2260.7056510074.2758.63228
10147.0660.5621410304.0559.2321810353.8861.87972 10411.360.37494 10491.462.91744
10548.4460.7830510571.25 61.750510605.4860.6835710633.4161.4701310741.7960.98887
10798.4963.9469910809.8362.3778710866.4464.4965810877.7164.0679210888.9859.20171
10911.5263.2072611024.2297.5082911035.4297.4697911046.6199.4690111116.69121.8688
#Mann= 3 , 0 , 0
 9320.96  0.0404       0 9320.96  0.0404       011116.69  0.0404       0
#XS Ineff= 2 , 0
       09463.726        10731.76       0
Bank Sta=9320.96,11116.69
Exp/Cntr=0.3,0.1

Type RM Length L Ch R = 1 ,22185.45,151.559900,151.559900,151.559900
XS GIS Cut Line= 3
923590.939980801827308.950981412924068.422703157826658.222315547
924681.121771667825525.785416509
#Sta/Elev= 30
9096.67161.269469204.95561.569599250.41159.90114 9509.2261.169839610.10659.72745
9858.17159.330919930.19160.86493   1007860.8774910282.6660.66212 10305.459.63858
 10339.561.4844210419.0960.1599610487.3161.3757310532.7960.1621710544.1661.59532
10657.8661.2500110714.7162.6801810737.1860.4711610800.2258.1382510817.0460.37804
10905.2963.5747610919.3762.0940210976.2263.6485910987.5962.5978710998.9558.12761
11010.3260.2850811135.3996.4898911146.7696.0373511157.4798.3824211191.35108.8526
#Mann= 3 , 0 , 0
9096.671    0.04       09096.671    0.04       011191.35    0.04       0
#XS Ineff= 2 , 0
       0 9498.52        10674.11       0
Bank Sta=9096.671,11191.35
Exp/Cntr=0.3,0.1

Type RM Length L Ch R = 1 ,22033.89,201.646500,201.646500,201.646500
XS GIS Cut Line= 6
923765.558312833827443.129334107924030.951772481827081.846252978
 924108.98279202826919.040792421924282.593903095826571.818570197
924638.496680915825929.457459092924833.809180915825582.235236883
#Sta/Elev= 30
9082.81460.070889385.91558.151229540.46559.732879583.04856.6380110301.9960.41418
10450.6159.8756710462.0458.5710610484.9159.0363810496.8561.1722710517.4961.92003
 10553.560.3556310610.6661.5191410644.9660.8488710667.8257.2499610690.6961.56606
10703.1961.6906110713.5560.7294410724.9857.2699610759.28 55.581810827.8757.70147
 10850.855.8204510862.2756.9467310873.7560.4702610885.2262.2400610977.0163.16243
11068.79 62.375311080.2761.9156211091.7459.3151111206.4892.54058 11232.694.84364
#Mann= 3 , 0 , 0
9082.814    0.04       09082.814    0.04       0 11232.6    0.04       0
#XS Ineff= 2 , 0
       0 9537.09        10599.92       0
Bank Sta=9082.814,11232.6
Exp/Cntr=0.3,0.1

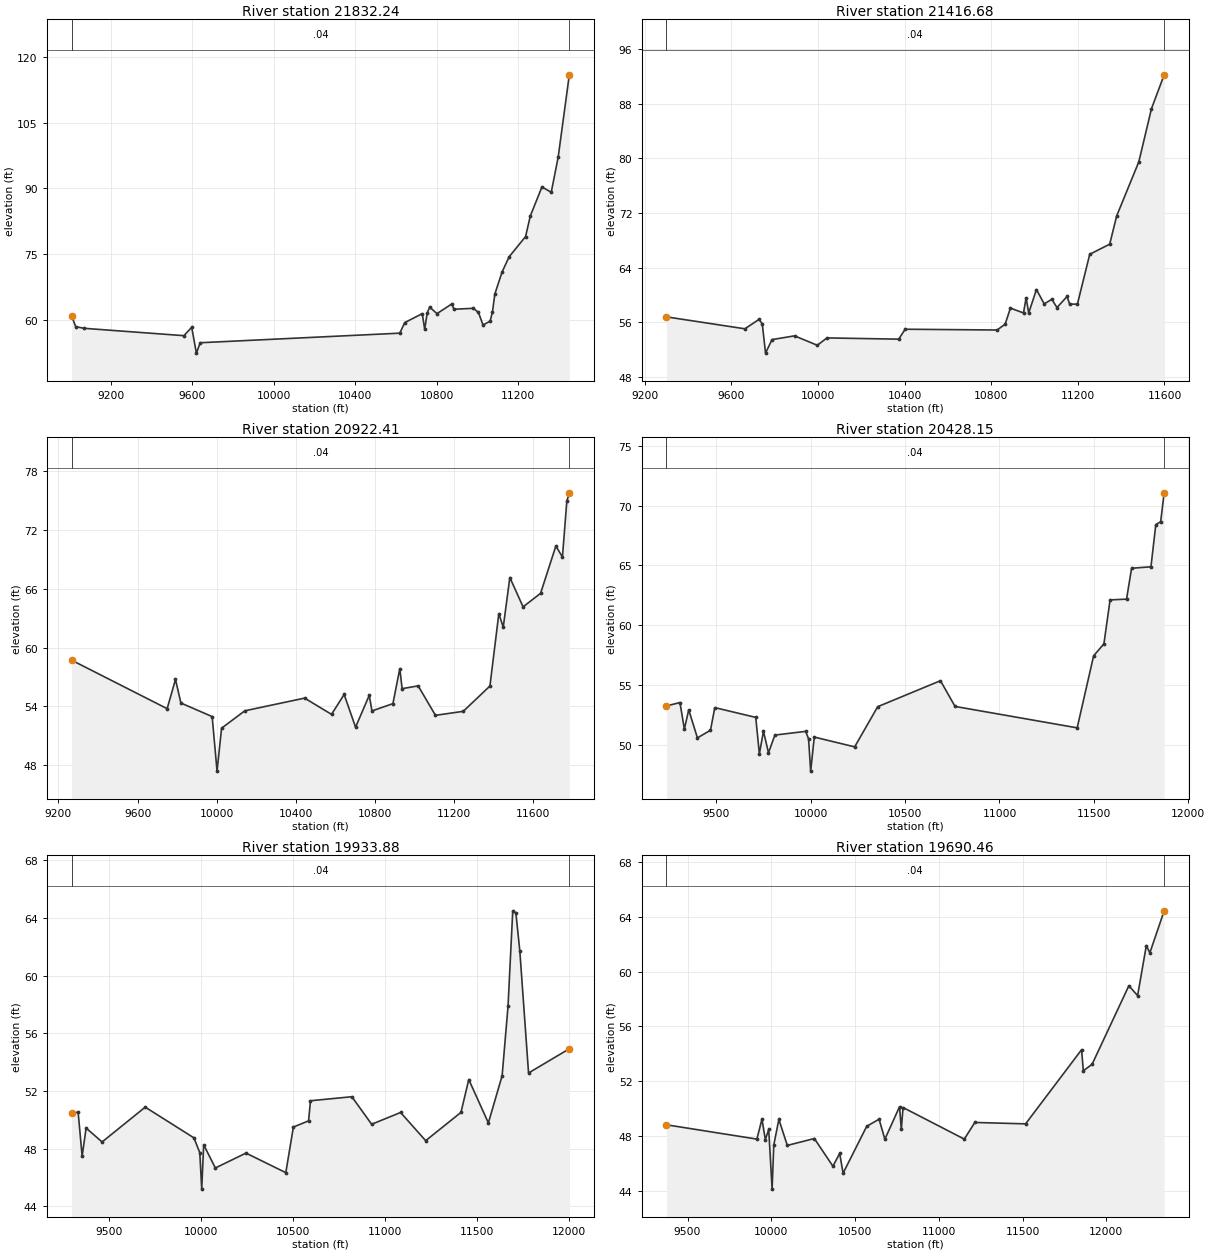
Type RM Length L Ch R = 1 ,21832.24,415.558500,415.558500,415.558500
XS GIS Cut Line= 6
923905.124392003827648.730757311 924101.97255221 827294.97464335
924660.939182311826324.260258362924760.083221227826186.365079954
924932.238804013825922.662658975925146.119592607825546.992177173
#Sta/Elev= 30
9008.10461.035819028.41458.544739069.59358.162569559.28556.485089597.54258.38953
9620.62152.511599639.44354.8785610618.3957.0564610642.8359.46305 10728.761.50623
10740.7757.9143910752.84 61.659210765.32 62.982610801.0661.5037210872.9963.69672
10884.83 62.509510979.58 62.716511004.3761.7867511026.7858.9187911061.6459.79405
11073.26 61.911511084.8865.9738411119.7370.9049811154.59 74.426711235.7679.06188
11258.6883.7222711315.9890.3520311361.6489.1380511395.7197.1741711450.23115.8836
#Mann= 3 , 0 , 0
9008.104    0.04       09008.104    0.04       011450.23    0.04       0
#XS Ineff= 2 , 0
       09586.899        10625.55       0
Bank Sta=9008.104,11450.23
Exp/Cntr=0.3,0.1

Type RM Length L Ch R = 1 ,21416.68,494.267500,494.267500,494.267500
XS GIS Cut Line= 6
924169.295293653827575.902231233924350.128309414827389.620090277
924894.148185172826886.648209619925086.244014243826676.923808779
925347.586769686826316.777450034925627.749715168825823.104267204
#Sta/Elev= 30
9300.25156.783339662.566 55.03599728.08756.41828 9743.0355.743539757.97251.47143
9787.85753.453059892.02654.00356 9997.0552.6198510041.4153.7001310372.9553.51713
10402.5454.97259 10827.354.8587610864.3255.7145410888.5858.0691110949.0757.35676
10961.03 59.577810972.9857.3567811008.8460.7859611044.6258.6840211079.88   59.36
11103.4658.1526411150.3559.7718511161.9958.6447111197.9658.65517 11254.965.95618
11346.9367.4335411379.4671.5921811481.4579.4993611539.9587.2901311598.46 92.2449
#Mann= 3 , 0 , 0
9300.251    0.04       09300.251    0.04       011598.46    0.04       0
#XS Ineff= 2 , 0
       09728.136        10665.59       0
Bank Sta=9300.251,11598.46
Exp/Cntr=0.3,0.1

Type RM Length L Ch R = 1 ,20922.41,494.267600,494.267600,494.267600
XS GIS Cut Line= 6
 924471.77234606 827998.21428054 924816.68478191827617.497816133
925101.988576311827375.874195814925341.352605875  827084.5202401
925599.283938461826681.572729589925947.587847681825993.523358569
#Sta/Elev= 30
9266.27458.716579749.50853.766169791.63856.748419819.068 54.34129977.03852.95763
10001.6447.3934910024.6151.7732510141.9153.54831 10444.354.8437510580.2553.18658
10644.1355.2132110701.8151.8765510770.9455.1265910784.8553.5351510890.6454.28065
10925.5157.8554910937.13 55.809711018.3456.0930511105.5953.0860811246.0453.49428
11380.9856.0753211425.97 63.465911448.2562.0789711481.6767.1497811548.5264.15528
11636.9565.5330411714.3170.3665611747.4769.2381511769.5774.9237111782.2575.79039
#Mann= 3 , 0 , 0
9266.274    0.04       09266.274    0.04       011782.25    0.04       0
#XS Ineff= 2 , 0
       0  9854.3        10353.05       0
Bank Sta=9266.274,11782.25
Exp/Cntr=0.3,0.1

Type RM Length L Ch R = 1 ,20428.15,494.267500,494.267500,494.267500
XS GIS Cut Line= 6
 925033.26587404828396.713762995925185.365756445828133.937975946
925328.931755739827863.417160063925650.037340116827197.556105735
925874.708912498826709.522145756926172.216050054826021.601883865
#Sta/Elev= 30
9236.27853.228829308.12853.516019331.41351.290769354.50152.906969400.54850.55764
9469.61951.195579492.64253.091799709.36652.273039728.58149.218689750.38751.11315
9776.88549.302159810.64450.79107 9973.6751.103319989.17250.47308 10000.347.77256
10019.4350.6248410233.2749.80471 10355.353.1689510687.63 55.344310764.9253.19058
11411.5951.3980211498.7257.4313711553.1858.4325211585.8562.1144811672.9962.17537
11699.7764.7626511802.2964.8850611827.9868.4204411853.6868.6615711872.2271.07968
#Mann= 3 , 0 , 0
9236.278    0.04       09236.278    0.04       011872.22    0.04       0
#XS Ineff= 2 , 0
       09688.322        10267.73       0
Bank Sta=9236.278,11872.22
Exp/Cntr=0.3,0.1

Type RM Length L Ch R = 1 ,19933.88,243.419200,243.419200,243.419200
XS GIS Cut Line= 6
925597.678263947828597.828822928925686.831417199828380.841143222
925878.067833229827829.080544512926021.374028945827266.480355207
926130.153089415826899.827354068926444.063535261826033.807101581
#Sta/Elev= 30
9298.00650.443359333.70550.538579355.453 47.48919377.20149.434439463.79748.46997
 9698.09 50.8839 9962.4648.755529994.28647.7311310004.8845.2021610015.4848.27759
 10078.946.6686410245.2347.6992810461.4346.3440610502.6149.5039910585.14 49.9345
10595.4751.3267710820.1251.6056710927.6349.6971911084.7950.5137311220.9148.56058
11412.5750.5196611455.0352.7960111561.4549.7921611636.1453.0598711668.1457.87263
11693.8464.4886111710.8264.3404511732.1661.7114911779.6153.2514212000.9754.92908
#Mann= 3 , 0 , 0
9298.006    0.04       09298.006    0.04       012000.97    0.04       0
#XS Ineff= 2 , 0
       09866.706        10384.32       0
Bank Sta=9298.006,12000.97
Exp/Cntr=0.3,0.1

Type RM Length L Ch R = 1 ,19690.46,250.848400,250.848400,250.848400
XS GIS Cut Line= 4
925906.519908686 828568.15320497926054.412787292828162.504166509
926164.276068542827334.304046316926658.660834167825703.256870835
#Sta/Elev= 30
9373.75748.811779913.97147.766829944.23349.225619964.40947.726789984.58448.47882
10004.7644.1145110014.8547.3384210045.1149.2028910095.5547.3061510256.9547.80929
10367.9145.7858210408.2646.7253710428.4445.2738610569.6648.7012410643.4849.22037
10677.9547.7585510765.6450.1327510776.0948.4767310786.5450.0727511152.2747.76605
11214.9648.9821311517.9948.8798211852.3754.2940711862.8252.7548111915.07 53.2308
 12134.558.9616412186.7558.2461612238.9961.9002712259.8961.3628312345.3164.43296
#Mann= 3 , 0 , 0
9373.757    0.04       09373.757    0.04       012345.31    0.04       0
#XS Ineff= 2 , 0
       09781.879        10312.47       0
Bank Sta=9373.757,12345.31
Exp/Cntr=0.3,0.1

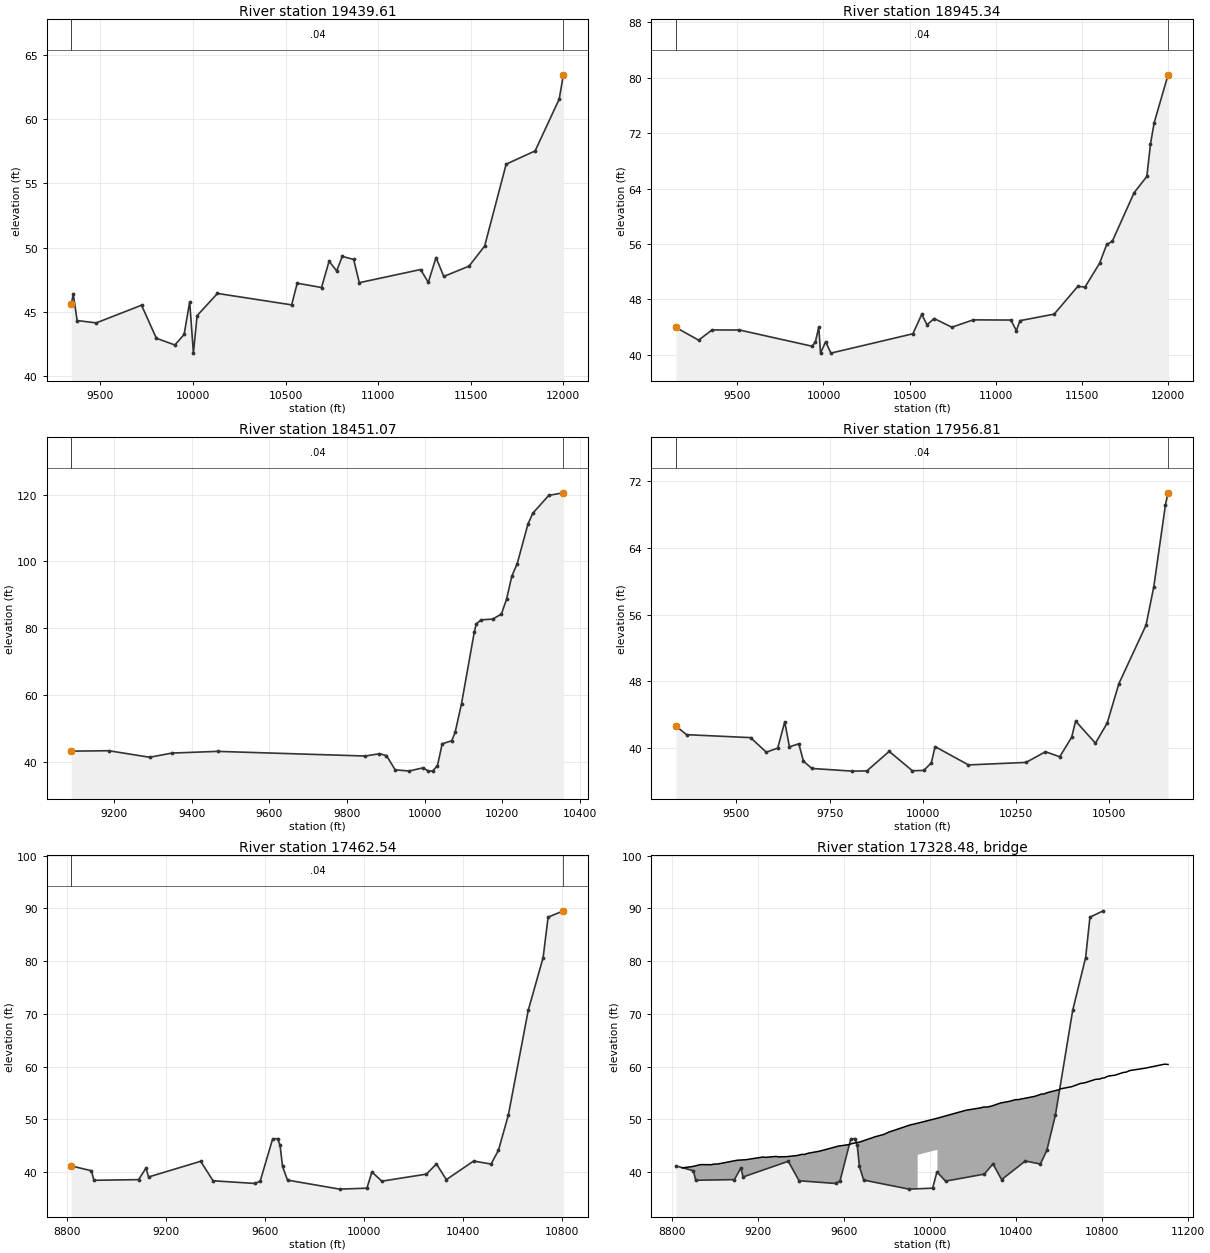
Type RM Length L Ch R = 1 ,19439.61,494.267500,494.267500,494.267500
XS GIS Cut Line= 6
926245.931414586828605.069696028926326.390706747828230.624067255
926328.996078168827593.638580799926378.438450289 827196.96053076
926509.864240504826679.653122358926736.066187523826013.807020978
#Sta/Elev= 30
9342.35145.554819352.95646.37267 9374.0244.300429477.51644.117049721.96845.49796
9802.13142.915259902.15242.392459952.158 43.21779982.16245.7652410002.1641.75616
10022.17 44.6831 10132.246.4161510532.94 45.523510563.1347.2152110694.5546.87849
10735.1948.9351410775.9148.1754810806.5849.3071610867.9149.0696110898.57 47.2543
 11229.548.2828811271.2247.2815311313.0449.2167411355.0347.7421611491.4948.54996
11575.6850.1173211691.9256.5069911848.4357.5429711978.4661.5875812000.9563.48172
#Mann= 3 , 0 , 0
9342.351    0.04       09342.351    0.04       012000.95    0.04       0
#XS Ineff= 2 , 0
       09646.556        10116.55       0
Bank Sta=9342.351,12000.95
Exp/Cntr=0.3,0.1

Type RM Length L Ch R = 1 ,18945.34,494.267600,494.267600,494.267600
XS GIS Cut Line= 6
926522.553147429828739.268277546926719.208344509828372.078986029
926786.689313756828193.337533575926853.520883314827677.914465332
926936.337384339827284.570094242927334.002763979826018.713174532
#Sta/Elev= 30
9143.31943.938229274.67742.105399352.997 43.58079512.07443.570299932.59141.23482
9952.66641.797899972.74243.98912 9982.7840.2496610012.8941.8754810043.0140.23014
 10519.2 43.026710570.5445.8297310601.3444.3212310642.4145.2293210745.56 43.9746
10869.8745.0375711088.6745.0085211120.0243.4788911140.9244.9216511339.8745.86435
11476.7249.8758911518.8249.7748811603.0353.2026111645.1455.9428811676.7256.35986
11803.7263.4025711877.8365.7569911899.0170.4521611920.1873.4977512000.9580.43703
#Mann= 3 , 0 , 0
9143.319    0.04       09143.319    0.04       012000.95    0.04       0
#XS Ineff= 2 , 0
       09455.171        10306.34       0
Bank Sta=9143.319,12000.95
Exp/Cntr=0.3,0.1

Type RM Length L Ch R = 1 ,18451.07,494.267500,494.267500,494.267500
XS GIS Cut Line= 6
926597.915966705828814.631096822926796.314436739828547.691432061
926943.537839422828393.447834698927032.192162701828320.208598521
927357.477588608828092.534154088927507.080767331827947.109531446
#Sta/Elev= 30
9090.024 43.15889186.75443.280869291.94741.324229349.28742.580249466.656 43.0882
9847.41441.694699883.64242.382939901.75541.821149924.142 37.55369960.12337.20836
9996.27638.1700810009.3837.1713110020.7937.2179310033.0138.8136610045.2445.34797
10069.69 46.269310078.4948.7654910094.9457.3578210127.8378.7953510132.6281.17169
10145.2282.4774710175.2782.7133610197.7784.2263310210.95 88.669210224.5495.56207
10238.4399.3265110266.21111.208510278.69114.434810319.69119.763610357.26120.5249
#Mann= 3 , 0 , 0
9090.024    0.04       09090.024    0.04       010357.26    0.04       0
#XS Ineff= 2 , 0
       09458.659        10352.03       0
Bank Sta=9090.024,10357.26
Exp/Cntr=0.3,0.1

Type RM Length L Ch R = 1 ,17956.81,494.267600,494.267600,494.267600
XS GIS Cut Line= 6
926865.879109867829006.236728648927208.563662063828711.791506968
927504.430624365828612.664684158927585.930075261 828555.78460846
 927691.16497066828438.122441791927779.611023029828158.258844296
#Sta/Elev= 30
9338.16642.597349366.63841.566059538.09841.21189 9580.3839.463249610.99839.95411
 9629.7943.107319642.34340.102389667.44840.47028    968038.378069702.52437.50931
9810.57137.187029849.93837.215869909.75939.558669972.05937.2332110002.53 37.2724
10022.7838.1835310032.9140.1297510122.3437.9334110276.8638.2348610328.8339.51659
10367.0738.9133310398.98 41.255210409.6243.19728 10462.840.5445910494.2842.95817
 10525.547.6876110598.3654.7215310619.1759.3272710650.3969.1715510657.41 70.6165
#Mann= 3 , 0 , 0
9338.166    0.04       09338.166    0.04       010657.41    0.04       0
#XS Ineff= 2 , 0
       0 9858.52        10310.54       0
Bank Sta=9338.166,10657.41
Exp/Cntr=0.3,0.1

Type RM Length L Ch R = 1 ,17462.54,323.992700,323.992700,323.992700
XS GIS Cut Line= 2
927735.435327768 829996.29606002927840.485847501828013.467500069
#Sta/Elev= 30
8818.989 41.16918900.39940.248548910.41338.445469090.66638.571219120.70840.76811
9130.72239.068319341.01642.047729391.08638.353619561.32537.837749581.353 38.2951
9631.42346.271649651.451 46.34499661.46545.066259671.47941.070859691.50738.48262
9901.80236.7690910011.9636.9493710031.9840.0266610072.0438.2801510252.2939.61484
10292.3541.55144 10332.438.5687510442.5642.0955110512.6641.52489 10542.744.12712
10582.7650.8486110662.8770.6699810722.9580.6770210742.9888.33398 10804.689.53339
#Mann= 3 , 0 , 0
8818.989    0.04       08818.989    0.04       0 10804.6    0.04       0
#XS Ineff= 2 , 0
       09822.109        10157.11       0
Bank Sta=8818.989,10804.6
Exp/Cntr=0.3,0.1

Type RM Length L Ch R = 3 ,17328.48,,,
BEGIN DESCRIPTION:
END DESCRIPTION:
Bridge Culvert--1,0,-1,-1, 0
Deck Dist Width WeirC Skew NumUp NumDn MinLoCord MaxHiCord MaxSubmerge Is_Ogee
99.496350,125.000000,2.6,0, 60, 60, , , 0.95, 0, 0,0,,
 8847.21 8893.93 8934.00 8984.10 8994.12 9014.15 9104.32 9144.40 9224.55 9234.56
 9284.66 9294.68 9334.75 9384.85 9404.88 9414.90 9434.94 9485.03 9575.20 9625.30
 9635.31 9675.39 9745.52 9785.59 9805.63 9905.82 9942.31 9942.3110034.3110034.31
10166.5210236.9710247.0010267.0710287.1410327.2910367.4310397.5310407.5710487.85
10517.9510527.9910548.0610598.2310608.2710658.4510698.5910718.6610768.8310788.90
10798.9410808.9710829.0410859.1510899.2910909.3310929.4010999.6411089.9611105.99
   40.80   41.04   41.42   41.40   41.51   41.54   42.25   42.35   42.86   42.79
   42.97   42.88   42.93   43.16   43.37   43.33   43.59   43.95   44.94   45.22
   45.39   45.73   46.71   47.15   47.54   48.92   49.27   49.27   50.22   50.22
   51.72   52.19   52.33   52.34   52.53   53.10   53.40   53.74   53.73   54.37
   54.80   54.80   55.10   55.61   55.80   56.19   56.80   56.92   57.58   57.64
   57.82   57.85   58.21   58.37   58.90   58.93   59.26   59.70   60.46   60.40
 -959.20 -958.96 -958.58 -958.60 -958.49 -958.46 -957.75 -957.65 -957.14 -957.21
 -957.03 -957.12 -957.07 -956.84 -956.63 -956.67 -956.41 -956.05 -955.06 -954.78
 -954.61 -954.27 -953.29 -952.85 -952.46 -951.08 -950.73   43.27   44.22 -949.78
 -948.28 -947.81 -947.67 -947.66 -947.47 -946.90 -946.60 -946.26 -946.27 -945.63
 -945.20 -945.20 -944.90 -944.39 -944.20 -943.81 -943.20 -943.08 -942.42 -942.36
 -942.18 -942.15 -941.79 -941.63 -941.10 -941.07 -940.74 -940.30 -939.54 -939.60
 8847.21 8893.93 8934.00 8984.10 9014.15 9104.32 9144.40 9224.55 9234.56 9284.66
 9294.68 9334.75 9384.85 9404.88 9414.90 9434.94 9485.03 9575.20 9625.30 9635.31
 9675.39 9745.52 9785.59 9805.63 9905.82 9960.34 9960.3410052.3410052.3410086.44
10126.5810166.5210236.9710247.0010267.0710327.2910367.4310397.5310407.5710487.85
10517.9510527.9910548.0610598.2310608.2710658.4510698.5910718.6610768.8310788.90
10798.9410808.9710829.0410859.1510899.2910909.3310929.4010999.6411089.9611105.99
   40.80   41.04   41.42   41.40   41.54   42.25   42.35   42.86   42.79   42.97
   42.88   42.93   43.16   43.37   43.33   43.59   43.95   44.94   45.22   45.39
   45.73   46.71   47.15   47.54   48.92   49.45   49.45   50.41   50.41   50.87
   51.23   51.72   52.19   52.33   52.34   53.10   53.40   53.74   53.73   54.37
   54.80   54.80   55.10   55.61   55.80   56.19   56.80   56.92   57.58   57.64
   57.82   57.85   58.21   58.37   58.90   58.93   59.26   59.70   60.46   60.40
 -959.20 -958.96 -958.58 -958.60 -958.46 -957.75 -957.65 -957.14 -957.21 -957.03
 -957.12 -957.07 -956.84 -956.63 -956.67 -956.41 -956.05 -955.06 -954.78 -954.61
 -954.27 -953.29 -952.85 -952.46 -951.08 -950.55   43.45   44.41 -949.59 -949.13
 -948.77 -948.28 -947.81 -947.67 -947.66 -946.90 -946.60 -946.26 -946.27 -945.63
 -945.20 -945.20 -944.90 -944.39 -944.20 -943.81 -943.20 -943.08 -942.42 -942.36
 -942.18 -942.15 -941.79 -941.63 -941.10 -941.07 -940.74 -940.30 -939.54 -939.60
BR Coef=-1 , 0 , 0 ,, 0 ,,,0.8,0,1,0,
WSPro=,,,, 1 ,,,, 0 ,,,, 0 ,,,,-1 ,-1 ,-1 , 0 , 0 , 0 , 0 , 0
BC Design=,, 0 ,, 0 ,,,,,,

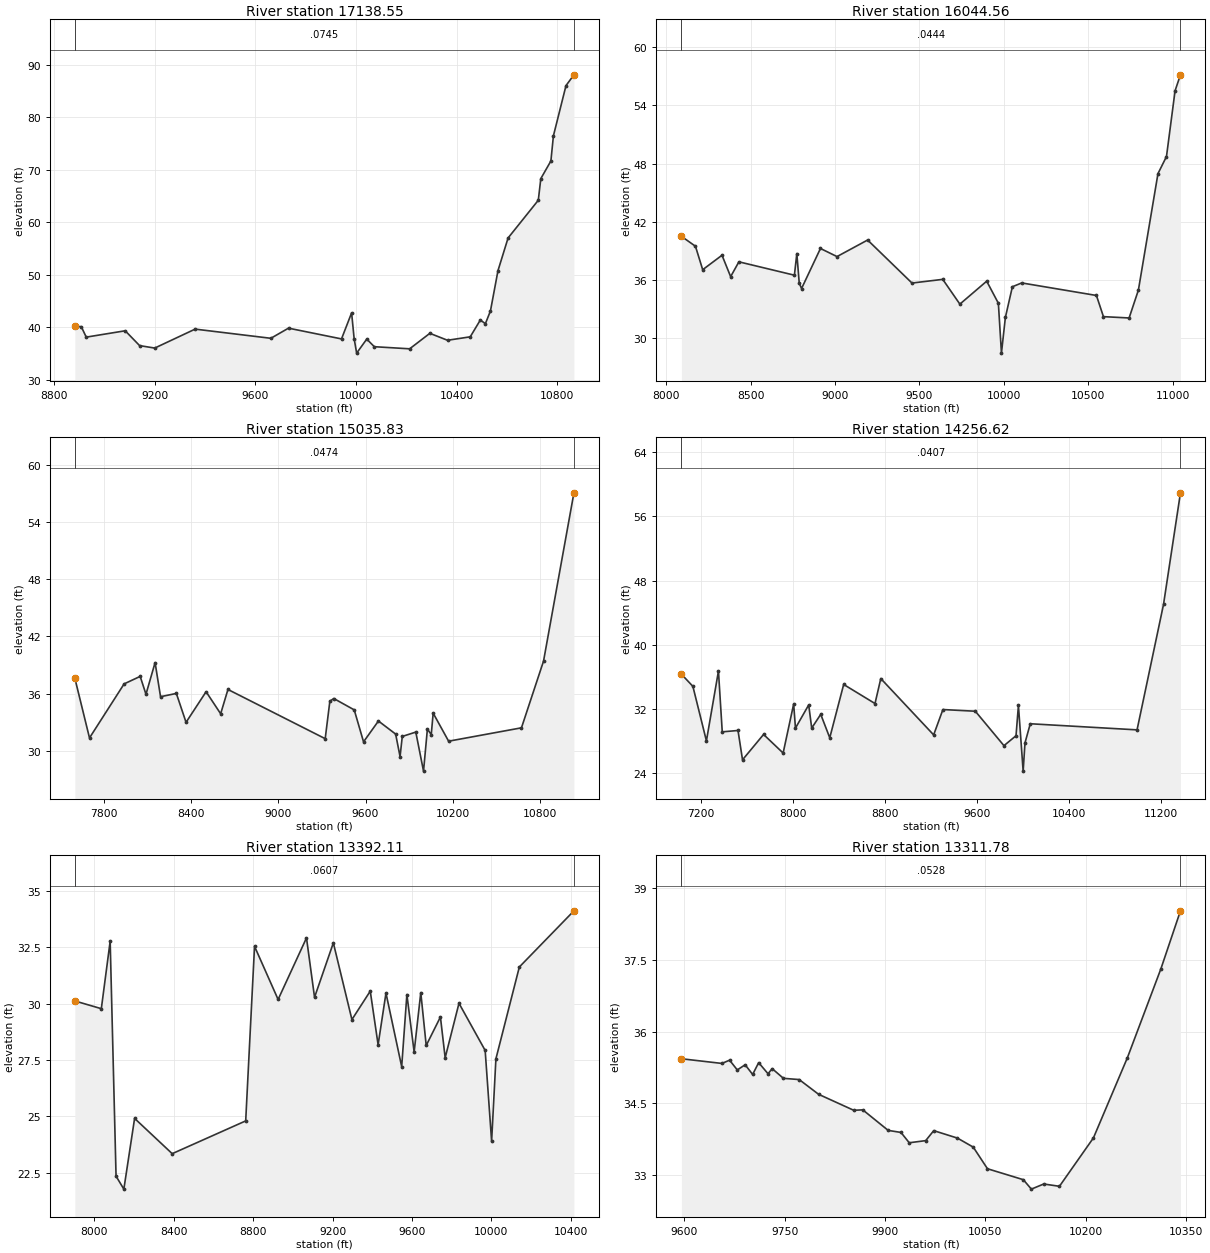
Type RM Length L Ch R = 1 ,17138.55,1093.984400,1093.984400,1093.984400
XS GIS Cut Line= 4
927921.952855331829927.090744064 928050.16508428829710.870845422
928166.169441251828280.150442779928179.966516571827983.513323386
#Sta/Elev= 30
8882.27440.209378907.85540.136838927.46138.149879082.34539.36042 9139.5436.53417
9199.73636.065849360.261 39.67729661.24637.927499731.47639.859759942.16537.80917
9982.29642.774639992.32937.8714710002.36 35.101910042.49 37.774910072.5936.32575
10213.0535.9234210293.3138.8751610363.5437.5509310453.8438.2083110493.9741.41194
10514.0440.71071 10534.143.12346 10564.250.8331910604.2557.0415110724.3864.23214
10734.3968.3533310774.4471.7148110784.4576.50043 10834.586.0783510866.0288.12928
#Mann= 3 , 0 , 0
8882.274  0.0745       08882.274  0.0745       010866.02  0.0745       0
#XS Ineff= 2 , 0
       09819.989        10153.31       0
Bank Sta=8882.274,10866.02
Exp/Cntr=0.3,0.1

Type RM Length L Ch R = 1 ,16044.56,1008.728500,1008.728500,1008.728500
XS GIS Cut Line= 3
927856.773164404830093.337136001928588.832562366829345.802080907
929906.995852813827965.117211467
#Sta/Elev= 30
8090.75240.512498173.97239.484888216.84937.069198331.18938.559528382.35136.35373
8431.23537.88145 8759.9636.503138774.25438.736538788.54535.686828802.24735.13003
8914.21939.257169012.19538.421779193.452 40.12889456.139 35.6942 9638.3436.07395
 9739.7133.52007 9898.5635.885519967.68833.611249985.89328.4701210009.1732.14958
10050.6435.3124410105.94 35.705510548.3734.4131610589.8432.2306810741.9232.09461
10796.8534.96807 10912.746.9696510963.1348.7339411014.0755.5191111045.9357.15661
#Mann= 3 , 0 , 0
8090.752  0.0444       08090.752  0.0444       011045.93  0.0444       0
#XS Ineff= 2 , 0
       09613.508                       0
Bank Sta=8090.752,11045.93
Exp/Cntr=0.3,0.1

Type RM Length L Ch R = 1 ,15035.83,779.214700,779.214700,779.214700
XS GIS Cut Line= 4
927804.689831071830655.837136001928706.520223708829974.532454292
929467.692968197 829366.25903839930342.692968197 828366.25903839
#Sta/Elev= 30
7600.22937.60269 7700.8831.338657939.00537.014388049.53537.80279  8089.435.92383
8152.06439.249738189.66335.667688298.379 36.01248365.12432.976088502.98536.19118
8603.24833.87518 8653.3836.427799322.41731.260159354.45435.192639381.37735.47946
9522.186 34.2846 9586.1930.926099688.59633.116279807.05631.742179837.42829.37581
9852.68231.496079945.69531.952229998.846 27.851710025.4232.26556   10052 31.6923
10065.2233.9395210171.5230.9961710672.6532.4003910824.5139.4105111033.61 57.0826
#Mann= 3 , 0 , 0
7600.229  0.0474       07600.229  0.0474       011033.61  0.0474       0
#XS Ineff= 2 , 0
       09417.355                       0
Bank Sta=7600.229,11033.61
Exp/Cntr=0.3,0.1

Type RM Length L Ch R = 1 ,14256.62,864.505500,864.505500,864.505500
XS GIS Cut Line= 5
927778.648164404831603.753802668929033.859544059830546.465541633
929759.359634864 829897.50903839930342.692968197829574.592371723
931123.942968197828862.786816168
#Sta/Elev= 30
 7031.39 36.31697131.21934.795617248.89227.98653 7353.4936.70253 7386.4729.11626
7523.46229.286227562.68725.624437745.73428.791597915.70626.468888007.22932.58284
8022.88829.583168137.97732.474988164.12729.585398242.57631.302228321.02428.37391
8441.99235.029548714.33332.649568764.74735.766639224.17428.735769304.67531.89957
9586.42931.689229835.27327.391159940.194 28.62979961.00232.4130410002.1424.21348
10018.15 27.741210064.08  30.12610992.2329.36333 11222.245.0114611369.5958.94915
#Mann= 3 , 0 , 0
 7031.39  0.0407       0 7031.39  0.0407       011369.59  0.0407       0
#XS Ineff= 2 , 0
       09214.903                       0
Bank Sta=7031.39,11369.59
Exp/Cntr=0.3,0.1

Type RM Length L Ch R = 1 ,13392.11,80.330800,80.330800,80.330800
XS GIS Cut Line= 6
928502.606497738831754.795469335929742.604450241830636.670857644
929941.651301531830503.411816168930224.637412642830380.147927279
930436.442968197830317.647927279930509.359634864830336.745149501
#Sta/Elev= 30
7901.66730.121728034.95929.778918079.49132.773568109.17922.343388148.46921.76916
8202.59424.908958392.03323.342778762.31224.797588806.84432.546398925.59530.18744
9068.59832.920229109.19130.284129203.91132.69936 9297.4529.294739389.83430.55866
9429.42728.17743 9469.0230.470199548.20627.206039574.35830.406629610.90327.85739
 9644.4130.492769671.73528.145979743.36729.410259767.24527.599959836.84630.01809
9968.73427.9258210001.2523.8965810022.9327.5543310140.9631.6294810415.9834.12247
#Mann= 3 , 0 , 0
7901.667  0.0607       07901.667  0.0607       010415.98  0.0607       0
#XS Ineff= 2 , 0
       09779.769                       0
Bank Sta=7901.667,10415.98
Exp/Cntr=0.3,0.1

Type RM Length L Ch R = 1 ,13311.78,45.532000,45.532000,45.532000
XS GIS Cut Line= 6
929897.814495975830817.647927279930041.043662642830574.158343945
930108.751995975830519.470843945930182.970745975830472.595843945
930276.720745975830440.043760612930464.220745975830417.908343945
#Sta/Elev= 30
9595.42435.430239656.00735.332239667.51435.400319679.02135.196179690.79235.30403
9702.03535.101679711.00335.34867 9725.0535.116139731.21435.223289748.06435.02039
9771.63734.994669800.695  34.6869853.24634.351589866.77934.360649904.76533.93086
9923.91133.887959936.239  33.6729960.89433.716619972.90933.9256110008.3933.76953
10032.0533.58032 10053.333.1281110106.9532.8989410118.9632.7015910137.4332.80876
10160.9732.7610310211.85 33.774810262.7235.4553710312.7737.31401   1034238.52618
#Mann= 3 , 0 , 0
9595.424  0.0528       09595.424  0.0528       0   10342  0.0528       0
#XS Ineff= 2 , 0
       09885.624                       0
Bank Sta=9595.424,10342
Exp/Cntr=0.3,0.1