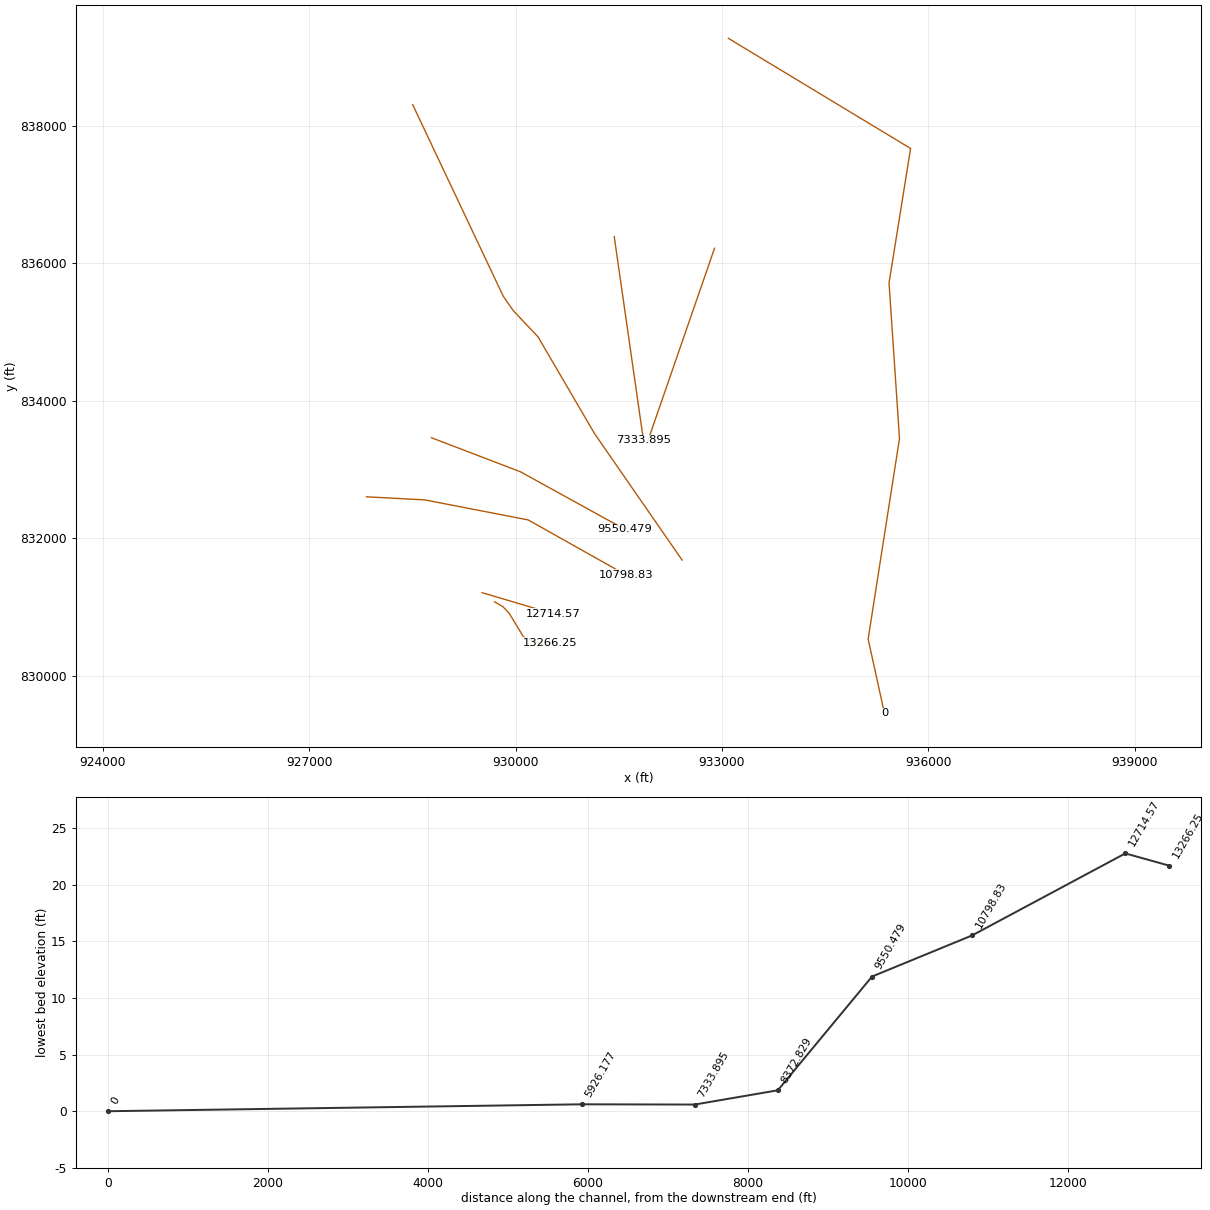
HEC-RAS study 16397_ras.prj: 16397

--- 16397_ras.g01 (geometry) --- (continued)

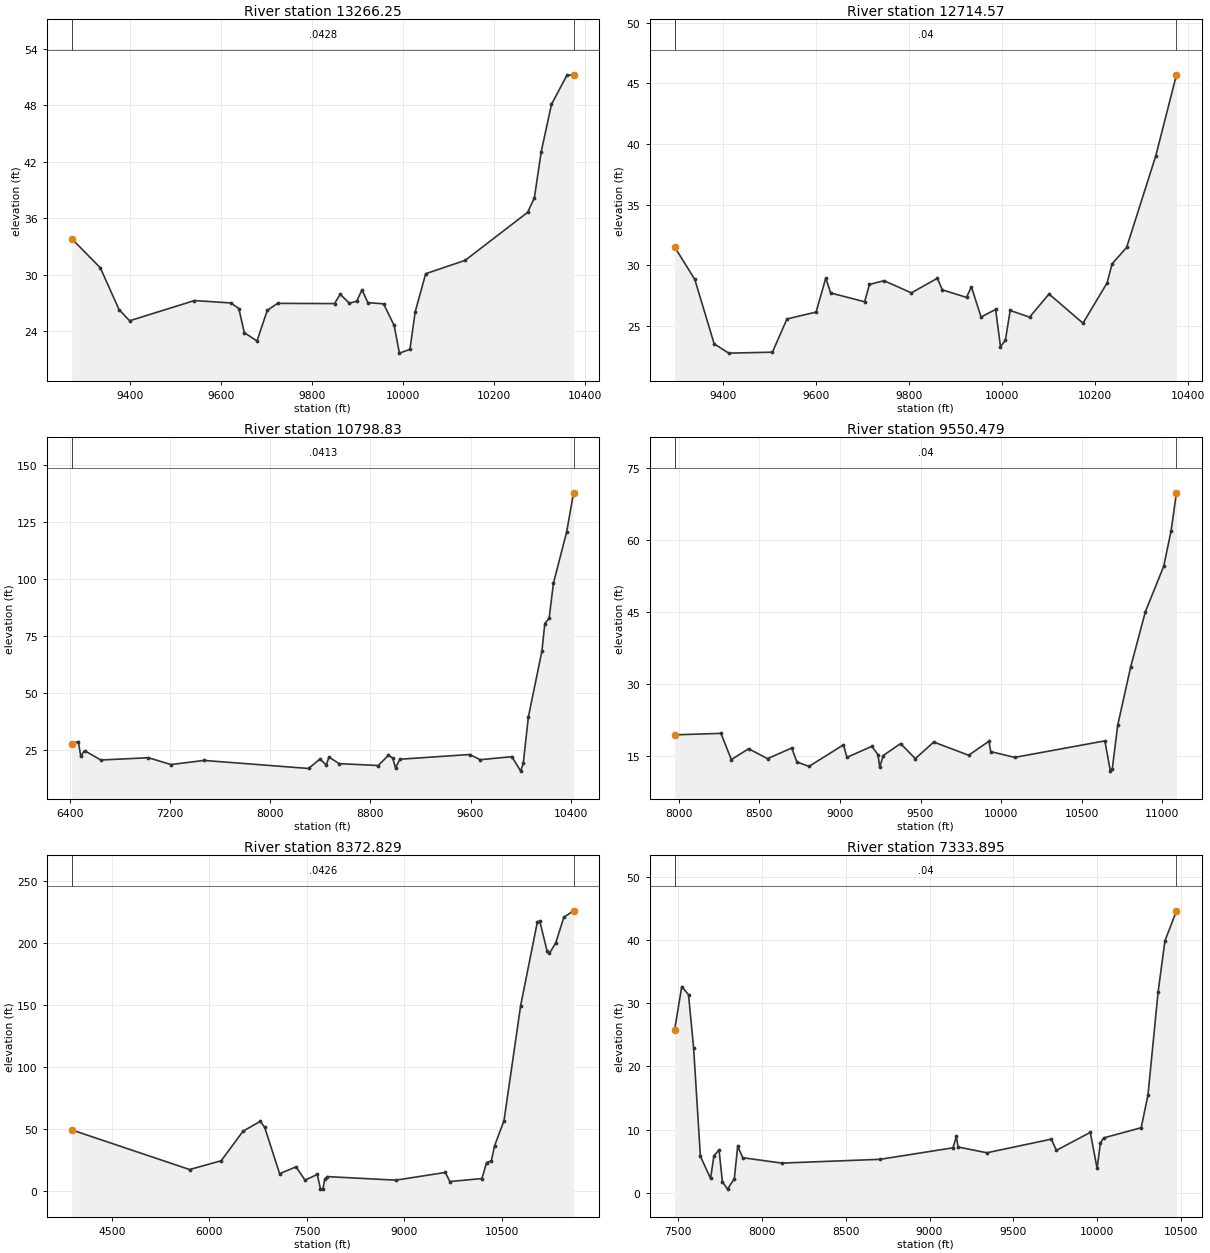
Type RM Length L Ch R = 1 ,13266.25,551.685100,551.685100,551.685100
XS GIS Cut Line= 6
 929695.55755153831076.979524501929818.821440419831004.062857834
929909.099218197830906.840635612930115.696440419830566.562857834
930431.668662641830441.562857834 930508.05755153 830481.49341339
#Sta/Elev= 30
9271.41433.825989334.22530.735519375.33426.303639398.57125.108379541.27927.25653
9621.36827.000459638.79226.409639650.819 23.84559678.75922.967399701.30626.20904
9723.85426.958069849.21526.934439861.74627.925679881.97626.970699898.07327.19688
9909.633 28.39969922.57427.037629957.19826.906959980.33724.610469991.90621.67149
10015.04 22.070510026.6126.0557610049.7530.1118710136.4131.5244110273.8936.62795
10288.6938.1660810303.7343.06293 10326.348.0960210360.1551.1855510374.88 51.2371
#Mann= 3 , 0 , 0
9271.414  0.0428       09271.414  0.0428       010374.88  0.0428       0
#XS Ineff= 2 , 0
       09865.579                       0
Bank Sta=9271.414,10374.88
Exp/Cntr=0.3,0.1

Type RM Length L Ch R = 1 ,12714.57,1915.735600,1915.735600,1915.735600
XS GIS Cut Line= 2
929513.512319211 831210.05843359930547.633094963830902.539807329
#Sta/Elev= 30
9295.96631.507769339.24928.83471 9380.9823.518629412.27922.757499506.17422.83567
9537.472 25.57729600.06926.142249620.93428.952739631.36727.716989704.39726.99227
9714.82928.419479746.128 28.72889804.87827.726839860.88828.928339871.32127.97639
9923.48527.350659933.91828.231029954.78325.731949986.08226.359229996.51523.29565
10006.9523.8008610017.3826.2751410059.1125.7237210100.8427.6341510173.8725.22557
10225.8828.5581310236.4730.1190510267.7731.4756510330.3639.0165110374.8445.70112
#Mann= 3 , 0 , 0
9295.966    0.04       09295.966    0.04       010374.84    0.04       0
#XS Ineff= 2 , 0
       09767.361                       0
Bank Sta=9295.966,10374.84
Exp/Cntr=0.3,0.1

Type RM Length L Ch R = 1 ,10798.83,1248.351800,1248.351800,1248.351800
XS GIS Cut Line= 4
 927832.99665845832603.509796313928680.907861977832558.453202387
930183.747469196832267.153895261931605.250010144831468.000725474
#Sta/Elev= 30
6412.68927.599376464.76628.492066484.79422.102076514.83724.51478 6645.0220.40744
7025.55621.40211 7205.8118.404657469.68820.21401 8304.9516.685258396.62520.81949
8447.55518.171858467.92821.739078549.41718.800858862.87617.97589 8943.1822.49346
8977.596 21.2695 9000.5416.964799034.95620.738059592.83122.815169677.38520.53401
9929.76821.8642410000.9515.5124810021.5418.9930610062.1739.3023310170.6868.32195
10193.6280.3801310228.0482.6599310262.45 98.069410368.25120.669910423.35137.8158
#Mann= 3 , 0 , 0
6412.689  0.0413       06412.689  0.0413       010423.35  0.0413       0
#XS Ineff= 2 , 0
       08536.236                       0
Bank Sta=6412.689,10423.35
Exp/Cntr=0.3,0.1

Type RM Length L Ch R = 1 ,9550.479,1177.649500,1177.649500,1177.649500
XS GIS Cut Line= 3
928776.389232139833462.347573968930070.593038076832967.296937817
931584.033554309832132.783008306
#Sta/Elev= 30
7974.37819.442948261.96919.753398326.20914.289018433.27516.549768551.04814.48573
8700.94116.71008 8733.0613.798578808.00712.879079022.13917.365789043.55214.76255
9198.52117.054299236.27215.307819246.97812.674449268.391 15.13519376.48517.61983
 9467.8414.492019582.03517.945259799.00515.199489924.61918.120359936.039 15.9521
10084.4914.7518310644.0518.18712 10678.311.8908110689.7212.2617610723.9821.48434
10803.9233.5393510895.2745.0553111009.4754.5607311055.1561.93575 11088.369.82526
#Mann= 3 , 0 , 0
7974.378    0.04       07974.378    0.04       0 11088.3    0.04       0
#XS Ineff= 2 , 0
       09504.462                       0
Bank Sta=7974.378,11088.3
Exp/Cntr=0.3,0.1

Type RM Length L Ch R = 1 ,8372.829,1038.933800,1038.933800,1038.933800
XS GIS Cut Line= 6
 928503.85287215838305.173513414929822.502085332835516.281672042
929966.068402999835310.051017713930325.547207342834930.109044546
931150.560026645833518.553318445932421.135242508831683.865261257
#Sta/Elev= 30
3878.84949.488085695.104 17.61016181.12824.708266517.557  48.4786783.29556.41019
 6850.9951.546947080.89514.250337334.11419.78818 7471.829.0852927661.28513.69188
7710.4661.8516177747.1981.847904 7777.039.8967557818.271 11.91838872.6599.061293
9632.38415.261159704.1727.94720810197.6810.3815110269.09 23.214710343.0524.68792
10391.6336.6114810537.7357.0224110793.54149.406311051.97217.034111088.85217.4038
 11199.6 193.74111236.68191.469111335.56200.131411459.16220.612511608.89225.7734
#Mann= 3 , 0 , 0
3878.849  0.0426       03878.849  0.0426       011608.89  0.0426       0
#XS Ineff= 2 , 0
       09422.602                       0
Bank Sta=3878.849,11608.89
Exp/Cntr=0.3,0.1

Type RM Length L Ch R = 1 ,7333.895,1407.717900,1407.717900,1407.717900
XS GIS Cut Line= 2
931434.345397781836386.828419207931859.009234921833426.858091682
#Sta/Elev= 30
7481.17525.817167523.43232.626127563.84231.350537594.14922.957327634.5585.793217
7695.1732.2800477715.3775.8827727745.6856.7841787765.8891.7497467796.197 0.58936
7836.6062.2233547856.8117.3626777887.118 5.559628119.4734.7066798705.4125.305879
9139.8157.124492 9160.028.9341499170.1227.2514239341.8636.3416289725.7548.495937
9756.061 6.724759958.1099.5661859998.5183.86658410018.727.95082910038.938.700856
10261.1810.3027710301.59 15.4357 10362.231.7905910402.6139.8477410471.4544.61419
#Mann= 3 , 0 , 0
7481.175    0.04       07481.175    0.04       010471.45    0.04       0
#XS Ineff= 2 , 0
       08587.871        10288.69       0
Bank Sta=7481.175,10471.45
Exp/Cntr=0.3,0.1

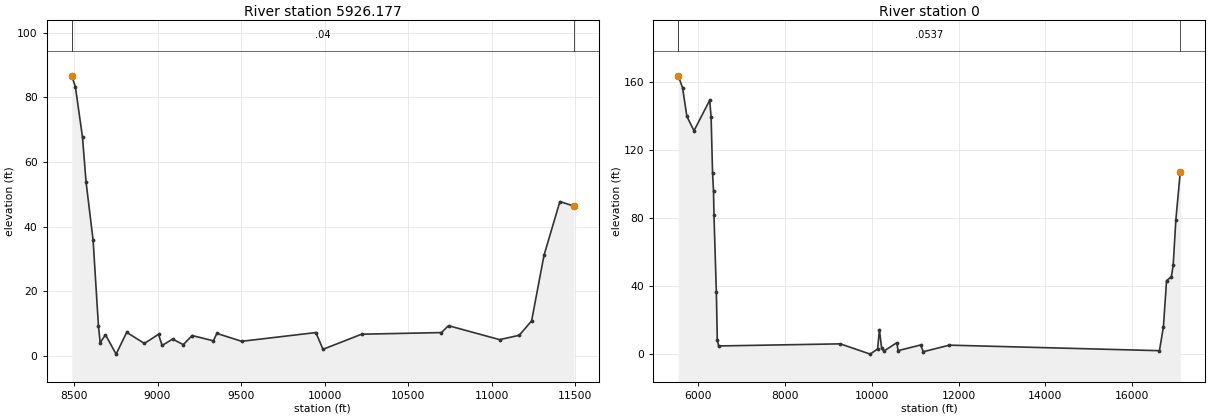
Type RM Length L Ch R = 1 ,5926.177,5926.177500,5926.177500,5926.177500
XS GIS Cut Line= 2
932892.146629752836215.695231106931909.715364728833376.151961875
#Sta/Elev= 30
8486.81986.638228508.67783.198548551.04567.636598572.20853.883748614.53435.79684
8646.2799.4400318656.8614.1408898688.6066.6124728752.095  0.61198815.5857.351041
8921.4013.9130569006.0546.7408049027.2173.2934779090.7075.2626429154.1963.543667
9207.1046.3670329334.084 4.726499355.2477.0155699503.3894.5774219947.8177.278903
9990.1432.10348310221.396.77148310699.117.27480310741.449.40630611047.175.089917
 11164.76.43487511238.77 10.891511312.8431.1405311408.0847.7790811491.5146.36926
#Mann= 3 , 0 , 0
8486.819    0.04       08486.819    0.04       011491.51    0.04       0
#XS Ineff= 2 , 0
       09076.241        10658.82       0
Bank Sta=8486.819,11491.51
Exp/Cntr=0.3,0.1

Type RM Length L Ch R = 1 ,       0,0.000000,0.000000,0.000000
XS GIS Cut Line= 6
933093.798187384  839268.6285545935743.036969435837667.566855782
935429.587319899835713.275585249935581.778956615833451.821663474
935125.801089408830536.228975114935362.928796358829454.926631423
#Sta/Elev= 30
5533.818163.35465633.889156.34775732.641139.57625897.228131.1173 6259.32149.0163
6292.238138.97576325.155106.4731  6347.195.831586358.07381.504186412.93536.26163
 6434.88 8.03701 6465.894.7974419271.7336.0283449961.333       0 10132.13.095216
10172.2714.3623810222.473.79976510272.681.74430210573.596.69751110603.632.054902
11123.885.37030711183.961.41341411787.03 5.2709816630.022.02291616722.1616.08758
16793.8243.1208716906.4345.4652216947.38 52.502517008.8178.9400817111.26107.1221
#Mann= 3 , 0 , 0
5533.818  0.0537       05533.818  0.0537       017111.26  0.0537       0
#XS Ineff= 2 , 0
       0                12399.42       0
Bank Sta=5533.818,17111.26
Exp/Cntr=0.3,0.1